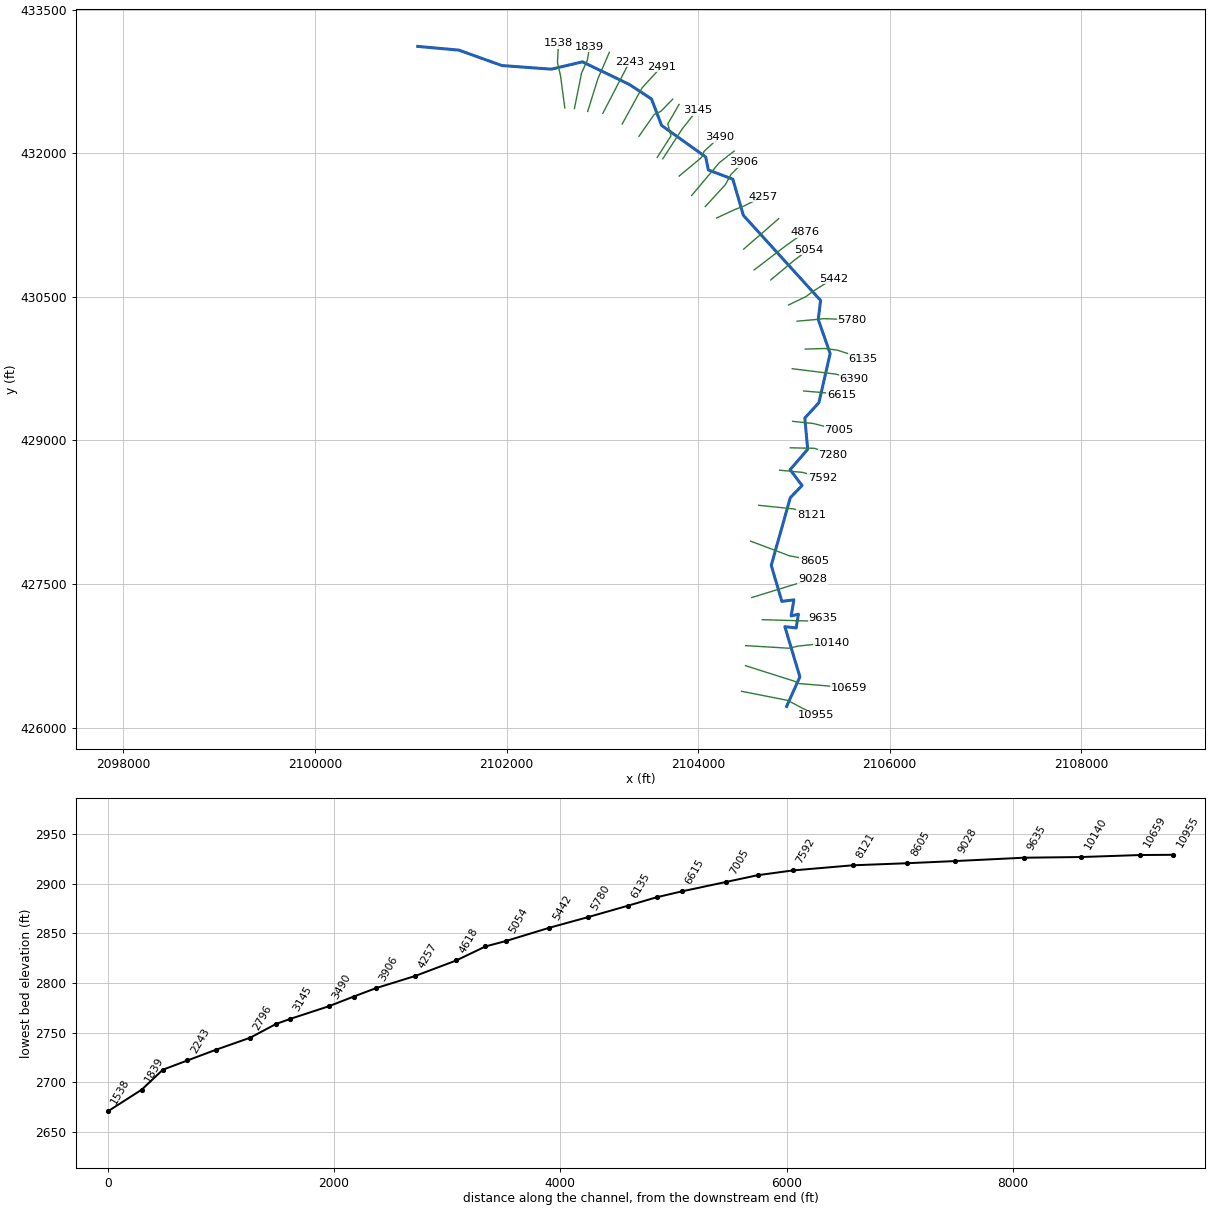
--- IMPRVMTBR.prj (project) ---

Proj Title=IMPRVMTBR
Current Plan=p01
Default Exp/Contr=0,0
English Units
Geom File=g01
Flow File=f01
Plan File=p01
BEGIN DESCRIPTION:
Stream Name- Improvement Branch
Flood Zone: Zone A
Greenbrier County, WV
County-Wide Study
WVDHSEM-2018-3, Flood Risk Project
HEC-RAS Version: 5.0.7
General Notes:
For the Hydrology Regression was used.
END DESCRIPTION:
DSS Export Rating Curves= 0
DSS Export Rating Curve Sorted= 0
DSS Export Volume Flow Curves= 0
DXF OffsetX= 0
DXF OffsetY= 0
DXF ScaleX= 0
DXF ScaleY= 0

--- IMPRVMTBR.p01 (plan) ---

Plan Title=Floodplain
Program Version=5.07
Short Identifier=Floodplain
Geom File=g01
Flow File=f01
Subcritical Flow
K Sum by GR= 0
Std Step Tol= 0.01
Critical Tol= 0.01
Num of Std Step Trials= 20
Max Error Tol= 0.3
Flow Tol Ratio= 0.001
Split Flow NTrial= 30
Split Flow Tol= 0.02
Split Flow Ratio= 0.02
Log Output Level= 0
Friction Slope Method= 1
Unsteady Friction Slope Method= 2
Unsteady Bridges Friction Slope Method= 1
Parabolic Critical Depth
Global Vel Dist= 0 , 0 , 0
Global Log Level= 0
CheckData=False
Encroach Param=-1 ,0,0, 0
Mapping Interval=1HOUR
Computation Time Step Use Courant=        0
Computation Time Step Use Time Series=    0
Computation Time Step Count To Double=0
Computation Time Step Max Doubling=0
Computation Time Step Max Halving=0
Computation Time Step Residence Courant=0
Run HTab= 0
Run UNet= 0
Run Sediment= 0
Run PostProcess= 0
Run WQNet= 0
Run RASMapper= 0
UNET Theta= 0
UNET Theta Warmup= 0
UNET ZTol= 0
UNET ZSATol= 0
UNET MxIter= 0
UNET Max Iter WO Improvement= 0
UNET MaxInSteps= 0
UNET DtIC= 0
UNET DtMin= 0
UNET MaxCRTS= 0
UNET WFStab= 0
UNET SFStab= 0
UNET WFX= 1
UNET SFX= 1
UNET 1D Methodology=Finite Difference
UNET DSS MLevel= 1
UNET Pardiso=0
UNET DZMax Abort= 0
UNET Use Existing IB Tables= 0
UNET Froude Reduction=False
UNET Froude Limit= 0
UNET Froude Power= 0
UNET D1 Cores= 0
UNET D2 Coriolis=0
UNET D2 Cores= 0
UNET D2 Theta= 1
UNET D2 Theta Warmup= 1
UNET D2 Z Tol= 0.01
UNET D2 Volume Tol= 0.01
UNET D2 Max Iterations= 20
UNET D2 Equation= 0
UNET D2 RampUpFraction=0.1
UNET D2 TimeSlices= 1
UNET D2 BCVolumeCheck=0
UNET D1D2 MaxIter= 0
UNET D1D2 ZTol=0.01
UNET D1D2 QTol=0.1
UNET D1D2 MinQTol=1
Write IC File= 0
Write IC File at Fixed DateTime=0
Write IC File at Sim End=0
Echo Input=False
Echo Parameters=False
Echo Output=False
Write Detailed= 0
HDF Write Warmup=0
HDF Write Time Slices=0
HDF Flush=0
HDF Face Node Velocities=0
HDF Compression= 1
HDF Chunk Size= 1
HDF Spatial Parts= 1
HDF Use Max Rows=0
HDF Fixed Rows= 1
Calibration Method= 0
Calibration Iterations= 20
Calibration Max Change=0.05
Calibration Tolerance=0.2
Calibration Maximum=1.5
Calibration Minimum=0.5
Calibration Optimization Method= 1
WQ AD Non Conservative
WQ ULTIMATE=-1
WQ Max Comp Step=1HOUR
WQ Output Interval=15MIN
WQ Output Selected Increments= 0
WQ Output face flow=0
WQ Output face velocity=0
WQ Output face area=0
WQ Output face dispersion=0
WQ Output cell volume=0
WQ Output cell surface area=0
WQ Output cell continuity=0
WQ Output cumulative cell continuity=0
WQ Output face conc=0
WQ Output face dconc_dx=0
WQ Output face courant=0
WQ Output face peclet=0
WQ Output face adv mass=0
WQ Output face disp mass=0
WQ Output cell mass=0
WQ Output cell source sink temp=0
WQ Output nsm pathways=0
WQ Output nsm derived pathways=0
WQ Output MaxMinRange=-1
WQ Daily Max Min Mean=-1
WQ Daily Range=0
WQ Daily Time=0
WQ Create Restart=0
WQ Fixed Restart=0
WQ System Summary=0
WQ Write To DSS=0
WQ Use Fixed Temperature=0
Sorting and Armoring Iterations= 10
XS Update Threshold= 0.02
Bed Roughness Predictor= 0
Hydraulics Update Threshold= 0.02
Energy Slope Method= 1
Volume Change Method= 1
Sediment Retention Method= 0
XS Weighting Method= 0
Number of US Weighted Cross Sections= 1
Number of DS Weighted Cross Sections= 1
Upstream XS Weight=0
Main XS Weight=1
Downstream XS Weight=0
Number of DS XS's Weighted with US Boundary= 1
Upstream Boundary Weight= 1
Weight of XSs Associated with US Boundary= 0
Number of US XS's Weighted with DS Boundary= 1
Downstream Boundary Weight= 0.5
Weight of XSs Associated with DS Boundary= 0.5
Percentile Method= 0
Sediment Output Level= 3
Mass or Volume Output= 0
Output Increment Type= 1
Profile and TS Output Increment= 1
XS Output Flag= 0
XS Output Increment= 10
Write Gradation File= 0
Read Gradation Hotstart= 0
Write HDF5 File= 1
Write Binary Output= 1
Write DSS Sediment File= 0
SV Curve= 0
Specific Gage Flag= 0

--- IMPRVMTBR.f01 (steady flow) ---

Flow Title=NFF Regression Equation
Program Version=5.07
Number of Profiles= 6
Profile Names=f1p,f10p,f4p,f2p,f02p,f1pplus
River Rch & RM=IMPRVMTBR,Main            ,10955
     341     177     237     287     481     504
River Rch & RM=IMPRVMTBR,Main            ,10659
     629     334     443     533     877     930
River Rch & RM=IMPRVMTBR,Main            ,7005
     705     376     498     598     981    1040
River Rch & RM=IMPRVMTBR,Main            ,4618
     784     419     555     666    1090    1160
Boundary for River Rch & Prof#=IMPRVMTBR,Main            , 1
Up Type= 0
Dn Type= 3
Dn Slope=0.029
Boundary for River Rch & Prof#=IMPRVMTBR,Main            , 2
Up Type= 0
Dn Type= 3
Dn Slope=0.029
Boundary for River Rch & Prof#=IMPRVMTBR,Main            , 3
Up Type= 0
Dn Type= 3
Dn Slope=0.029
Boundary for River Rch & Prof#=IMPRVMTBR,Main            , 4
Up Type= 0
Dn Type= 3
Dn Slope=0.029
Boundary for River Rch & Prof#=IMPRVMTBR,Main            , 5
Up Type= 0
Dn Type= 3
Dn Slope=0.029
Boundary for River Rch & Prof#=IMPRVMTBR,Main            , 6
Up Type= 0
Dn Type= 3
Dn Slope=0.029
DSS Import GetInterval= 0
DSS Import GetPeak= 0
DSS Import FillOption= 0

--- IMPRVMTBR.g01 (geometry) ---

Geom Title=USGS 10m DEM
Program Version=5.07

River Reach=IMPRVMTBR       ,Main
Reach XY= 30
2104923.25988089426220.6338415592105061.90396056  426529.3550089
2104905.00499614427053.8254166392105022.82595472427040.523277894
 2105046.5801723427183.9987127332104970.56687288427165.945599228
2104999.07173714427334.1253809782104873.64941581427317.972526148
2104762.91735381427695.1092390572104961.82902947428401.115044892
2105084.33797081428528.5609842242104959.95206472428693.773908392
2105143.38214405428906.5861468172105113.39007805 429232.97492972
2105260.31694956429393.7410123942105377.83902422 429906.82594423
2105253.95114864430261.3869148942105277.79394872430461.978049144
 2104471.3588818431351.3748923992104362.18685606431728.186146647
2104106.66407314431824.4251273872104078.32859636431960.540876961
2103618.04497163432290.187975392 2103513.1029243432566.289129227
2103280.91506848432718.3698618112102791.90095463432954.057054475
2102467.51085539 432877.655960562101952.07094139432915.093877807
2101500.74568417433076.7534363052101072.64947189433115.274579808

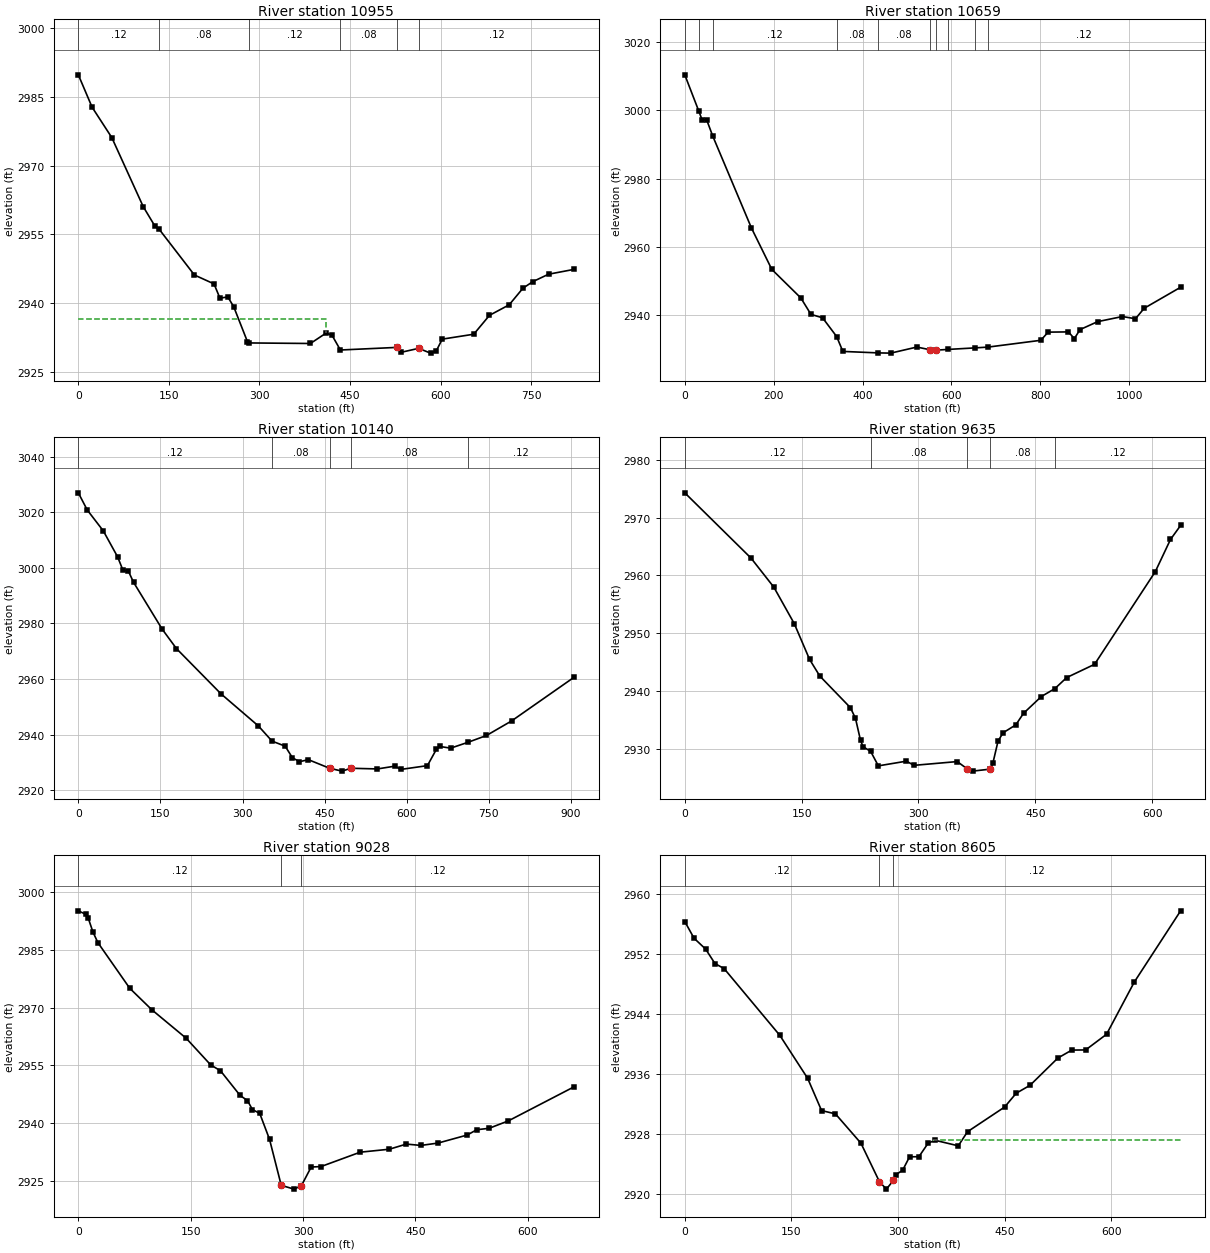
Type RM Length L Ch R = 1 ,10955   ,291.7,295.6,280.4
XS GIS Cut Line= 4
      2104452.96      426378.557     2104862.076      426298.512
      2104935.45      426282.948     2105226.724       426129.53
#Sta/Elev= 30
       0  2989.8    22.8 2982.74    55.4 2976.13   107.5 2961.06     127 2956.79
  132.93  2956.3   192.2 2946.17   224.7 2944.23   234.5 2941.12   247.5 2941.39
   257.3 2939.26   280.1 2931.62  283.41 2931.36   384.3 2931.24   410.4 2933.52
   420.1 2933.04  433.95 2929.82   527.7 2930.39   534.2 2929.31   563.6 2930.18
   583.2 2929.14   592.9 2929.67   602.7 2932.19   654.8 2933.26   680.9 2937.38
   713.5 2939.67   736.3 2943.29   752.6 2944.72   778.7 2946.34   821.1  2947.4
#Mann= 6 ,-1 , 0
       0     .12       0  132.93     .08       0  283.41     .12       0
  433.95     .08       0   527.7     .04       0   563.6     .12       0
#XS Ineff= 2 , 0
          409.75 2936.64
Permanent Ineff=
       F       F
Bank Sta=527.7,563.6
XS Rating Curve= 0 ,0
Exp/Cntr=0.3,0.1

Type RM Length L Ch R = 1 ,10659   ,502.5,519.5,508
XS GIS Cut Line= 4
     2104494.093      426646.484     2105001.042      426485.283
      2105051.07      426459.713     2105576.918      426416.356
#Sta/Elev= 30
       0 3010.41   31.74  2999.7    39.2 2997.12      49  2997.3   62.74 2992.52
   150.1 2965.51   195.8 2953.42   261.1 2945.06   283.9 2940.24     310 2939.24
  341.68 2933.76   355.7 2929.39  434.66 2928.96   463.4 2928.89   522.2 2930.67
   550.7 2929.91   566.3 2929.77  593.09 2929.98  652.37 2930.42     682 2930.65
   801.2 2932.65   817.6 2935.04   863.4 2935.11   876.5 2933.14   889.6 2935.79
     929 2938.11   984.7 2939.61  1014.2 2938.96  1033.8 2942.03  1115.8 2948.19
#Mann= 10 ,-1 , 0
       0     .12       0   31.74     .06       0   62.74     .12       0
  341.68     .08       0  434.66     .08       0   550.7     .04       0
   566.3     .08       0  593.09     .12       0  652.37     .08       0
     682     .12       0
Bank Sta=550.7,566.3
XS Rating Curve= 0 ,0
Exp/Cntr=0.3,0.1

Type RM Length L Ch R = 1 ,10140   ,486,504.6,447.5
XS GIS Cut Line= 4
     2104495.997      426855.679     2104948.048      426828.664
     2105045.302      426851.177     2105396.498      426888.097
#Sta/Elev= 30
       0 3026.94    16.3 3020.76    45.6 3013.26    71.7 3003.94    81.4 2999.17
    91.2 2998.87     101 2994.73   153.1 2977.94   179.2 2970.95   260.6 2954.67
     329 2943.11  353.88 2937.67   377.9 2935.85     391 2931.71     404 2930.27
   420.3    2931   459.3 2927.89   481.8 2926.88   497.9 2927.91   546.2 2927.67
   578.8 2928.68   588.6 2927.48   637.7 2928.85     654 2934.68   660.6 2935.74
   680.2 2935.14  711.94 2937.25   745.6 2939.69   791.4 2944.91   905.8 2960.65
#Mann= 5 ,-1 , 0
       0     .12       0  353.88     .08       0   459.3     .04       0
   497.9     .08       0  711.94     .12       0
Bank Sta=459.3,497.9
XS Rating Curve= 0 ,0
Exp/Cntr=0.3,0.1

Type RM Length L Ch R = 1 ,9635    ,605.6,607.4,556.9
XS GIS Cut Line= 3
     2104669.794       427126.73     2105137.153      427113.222
     2105303.746      427142.038
#Sta/Elev= 30
       0 2974.27      85    2963   114.4 2957.96   140.6 2951.66   160.2  2945.5
   173.3 2942.63   212.5 2937.18   219.1 2935.34   225.6 2931.52   228.9 2930.42
  238.62 2929.61   248.5 2927.11   284.5 2927.92   294.3  2927.2   349.8 2927.85
   362.9 2926.56   369.5  2926.2   392.4 2926.55   395.6 2927.61   402.2  2931.4
   408.7 2932.83     425 2934.19   434.9 2936.19   457.8 2939.09  475.12 2940.45
   490.3 2942.36   526.1 2944.65   604.1 2960.66   623.6 2966.22   636.6 2968.64
#Mann= 5 ,-1 , 0
       0     .12       0  238.62     .08       0   362.9     .04       0
   392.4     .08       0  475.12     .12       0
Bank Sta=362.9,392.4
XS Rating Curve= 0 ,0
Exp/Cntr=0.3,0.1

Type RM Length L Ch R = 1 ,9028    ,429,422.8,414.3
XS GIS Cut Line= 3
     2104559.933      427358.158     2104903.924      427464.418
     2105192.985      427551.766
#Sta/Elev= 30
       0 2995.23     9.8 2994.34    13.1  2993.4    19.6 2989.67    26.2 2986.93
    68.7 2975.07    98.2 2969.48     144 2962.08   176.7 2955.15   189.8 2953.62
     216  2947.2   225.8 2945.87   232.4 2943.54   242.2 2942.53   255.3 2935.77
   270.9 2923.82     288 2922.83   297.8 2923.71   310.9 2928.58     324  2928.7
   376.3 2932.44   415.2 2933.21     438 2934.55   457.4  2934.2   480.2 2934.81
   519.1  2936.9   532.1 2938.29   548.4 2938.65   574.3  2940.6     662 2949.46
#Mann= 3 , 0 , 0
       0     .12       0   270.9     .04       0   297.8     .12       0
Bank Sta=270.9,297.8
XS Rating Curve= 0 ,0
Exp/Cntr=0.3,0.1

Type RM Length L Ch R = 1 ,8605    ,477.9,483.9,484.6
XS GIS Cut Line= 3
     2104548.226      427947.086      2104950.75      427794.902
     2105212.796      427742.672
#Sta/Elev= 30
       0 2956.31      13 2954.09    29.3 2952.64    42.4 2950.72    55.4 2950.03
   133.7 2941.14   172.8 2935.42   192.4 2931.12   211.9 2930.68   247.8 2926.77
   273.8 2921.64   283.6 2920.65   293.4  2921.8   296.7 2922.56   306.4 2923.16
   316.2 2924.96   329.3 2924.97   342.3 2926.77   352.1 2927.16   384.7 2926.42
   397.7  2928.3   449.9 2931.59   466.2 2933.43   485.7 2934.49   524.8 2938.12
   544.4 2939.18   563.9  2939.2   593.3 2941.29   632.4 2948.26   697.5 2957.74
#Mann= 3 ,-1 , 0
       0     .12       0   273.8     .04       0   293.4     .12       0
#XS Ineff= 2 , 0
                          349.24         2927.26
Permanent Ineff=
       F       F
Bank Sta=273.8,293.4
XS Rating Curve= 0 ,0
Exp/Cntr=0.3,0.1

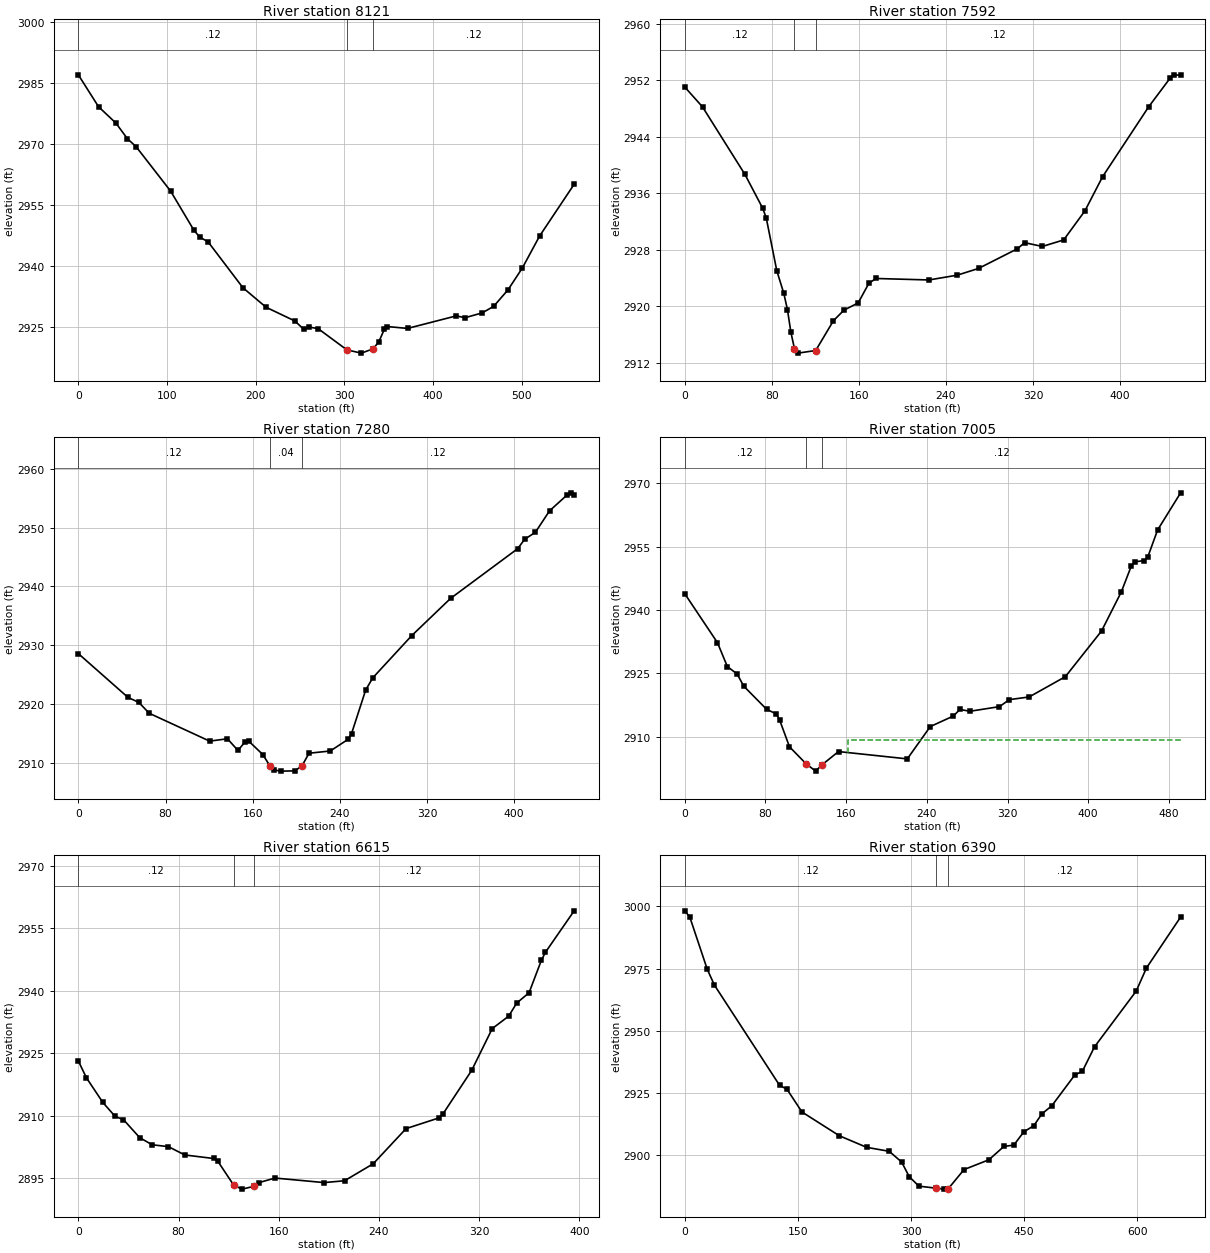
Type RM Length L Ch R = 1 ,8121    ,521,528.8,521.5
XS GIS Cut Line= 3
     2104632.873      428321.695     2104995.775      428283.873
     2105181.278      428225.341
#Sta/Elev= 30
       0 2987.03    22.8 2979.18    42.4 2975.15    55.4  2971.3    65.2 2969.34
   104.2 2958.39   130.3 2948.82   136.8 2947.14   146.6 2945.87   185.7 2934.63
   211.8 2929.83   244.3 2926.45   254.1 2924.45   260.6 2924.93   270.4 2924.59
     303 2919.34   319.3 2918.54   332.3 2919.57   338.8 2921.22   345.3 2924.44
   348.6 2925.08   371.4 2924.62   426.5 2927.71   436.2 2927.25   455.6 2928.44
   468.6 2930.05   484.8 2934.13     501 2939.51   520.5 2947.39   559.4  2960.1
#Mann= 3 ,-1 , 0
       0     .12       0     303     .04       0   332.3     .12       0
Bank Sta=303,332.3
XS Rating Curve= 0 ,0
Exp/Cntr=0.3,0.1

Type RM Length L Ch R = 1 ,7592    ,312.6,312.2,320.4
XS GIS Cut Line= 3
     2104849.894      428688.198     2105089.427      428665.686
     2105296.542      428608.054
#Sta/Elev= 30
       0 2951.01    16.3  2948.2    55.3 2938.64    71.5 2933.89    74.8 2932.53
    84.5 2925.05      91 2921.81    94.3 2919.54    97.5 2916.31   100.8 2913.97
     104 2913.37   120.3 2913.74   136.6 2917.96   146.3 2919.46   159.3 2920.47
   169.1 2923.24   175.6 2923.93   224.3 2923.72   250.4  2924.4   269.9 2925.35
   305.7 2928.14   312.2    2929   328.5 2928.46   348.1 2929.38   367.6 2933.48
   383.9 2938.33   426.3 2948.23   445.8 2952.24   449.1 2952.74   455.6 2952.68
#Mann= 3 ,-1 , 0
       0     .12       0   100.8     .04       0   120.3     .12       0
Bank Sta=100.8,120.3
XS Rating Curve= 0 ,0
Exp/Cntr=0.3,0.1

Type RM Length L Ch R = 1 ,7280    ,275.3,275.3,276
XS GIS Cut Line= 3
     2104961.556      428922.329     2105215.497      428916.926
     2105405.503      428851.189
#Sta/Elev= 30
       0 2928.57    45.6  2921.1    55.4 2920.27    65.1  2918.4   120.5 2913.66
   136.8 2914.06   146.5 2912.07     153 2913.53   156.3 2913.68   169.3 2911.37
   175.8 2909.44   179.1 2908.77   185.6 2908.55   198.6 2908.59   205.2 2909.43
   211.7  2911.6   231.2 2911.98   247.5 2913.96   250.7 2914.93   263.7 2922.37
   270.2 2924.44   305.9 2931.62   341.6 2937.97   403.2 2946.44   409.6 2948.05
   419.4 2949.22   432.4 2952.88   448.6  2955.6   451.8 2955.95     455  2955.5
#Mann= 3 ,-1 , 0
       0     .12       0   175.8     .04       0   205.2     .12       0
Bank Sta=175.8,205.2
XS Rating Curve= 0 ,0
Exp/Cntr=0.3,0.1

Type RM Length L Ch R = 1 ,7005    ,385.5,390.1,386.4
XS GIS Cut Line= 3
     2104985.869      429198.783      2105201.99       429176.27
     2105467.637      429107.832
#Sta/Elev= 30
       0 2943.81    32.4 2932.23    42.2 2926.57    51.9 2924.82    58.4 2921.95
    81.1 2916.46    90.8 2915.35      94 2913.94   103.8 2907.58     120 2903.62
   129.7 2901.82   136.2 2903.35   152.4 2906.45   220.6 2904.72   243.4 2912.37
   266.3 2914.87   272.8 2916.43   282.6 2915.99     312 2917.09   321.8 2918.75
   341.4 2919.38   377.3 2924.18   413.2    2935   432.8 2944.26   442.6 2950.32
   445.9 2951.37   455.7 2951.67     459  2952.5   468.8 2958.93   491.6 2967.71
#Mann= 3 ,-1 , 0
       0     .12       0     120     .04       0   136.2     .12       0
#XS Ineff= 2 , 0
                          161.68         2909.27
Permanent Ineff=
       F       F
Bank Sta=120,136.2
XS Rating Curve= 0 ,0
Exp/Cntr=0.3,0.1

Type RM Length L Ch R = 1 ,6615    ,225.7,224.8,225.1
XS GIS Cut Line= 3
     2105101.134      429515.759     2105348.771      429495.048
     2105494.652      429474.336
#Sta/Elev= 30
       0 2923.12     6.5 2919.06    19.6 2913.15    29.4  2909.8      36 2909.04
      49 2904.71    58.9    2903    71.9 2902.55      85 2900.55   107.9 2899.71
   111.2 2899.11   124.2 2893.23   130.8 2892.35   140.6 2893.06   143.9 2893.89
     157 2895.01   196.2 2893.92   212.5 2894.36   235.4 2898.44   261.6 2906.88
   287.8 2909.44   291.1 2910.42     314 2920.86   330.4 2930.89   343.5 2933.87
     350 2937.04   359.8  2939.5   369.6 2947.27   372.9 2949.23   395.8 2959.17
#Mann= 3 ,-1 , 0
       0     .12       0   124.2     .04       0   140.6     .12       0
Bank Sta=124.2,140.6
XS Rating Curve= 0 ,0
Exp/Cntr=0.3,0.1

Type RM Length L Ch R = 1 ,6390    ,254.9,255.4,255.1
XS GIS Cut Line= 3
2104982.26527488429748.4634552542105436.72519306429691.899774451
2105629.82189649429641.187508904
#Sta/Elev= 30
       0  2998.2     6.6 2995.72    29.8 2974.69    39.3 2968.35   125.6 2928.14
   135.6 2926.47   155.4 2917.37     205 2907.82   241.3 2903.16   271.1 2901.58
   287.6 2897.27   297.6 2891.41   310.4 2887.58   333.72886.748   343.8 2886.38
   349.52886.563   370.3 2894.23   403.3 2898.17   423.2 2903.53   436.4 2904.07
   449.6  2909.4   462.9 2911.86   473.6 2916.63   486.7 2919.85   517.3 2932.27
   527.3 2933.73   543.4 2943.56   598.7 2965.96   612.2 2975.19   657.6  2995.7
#Mann= 3 , 0 , 0
       0     .12       0   333.7     .04       0   349.5     .12       0
Bank Sta=333.7,349.5
XS Rating Curve= 0 ,0
Exp/Cntr(USF)=0,0
Exp/Cntr=0.3,0.1

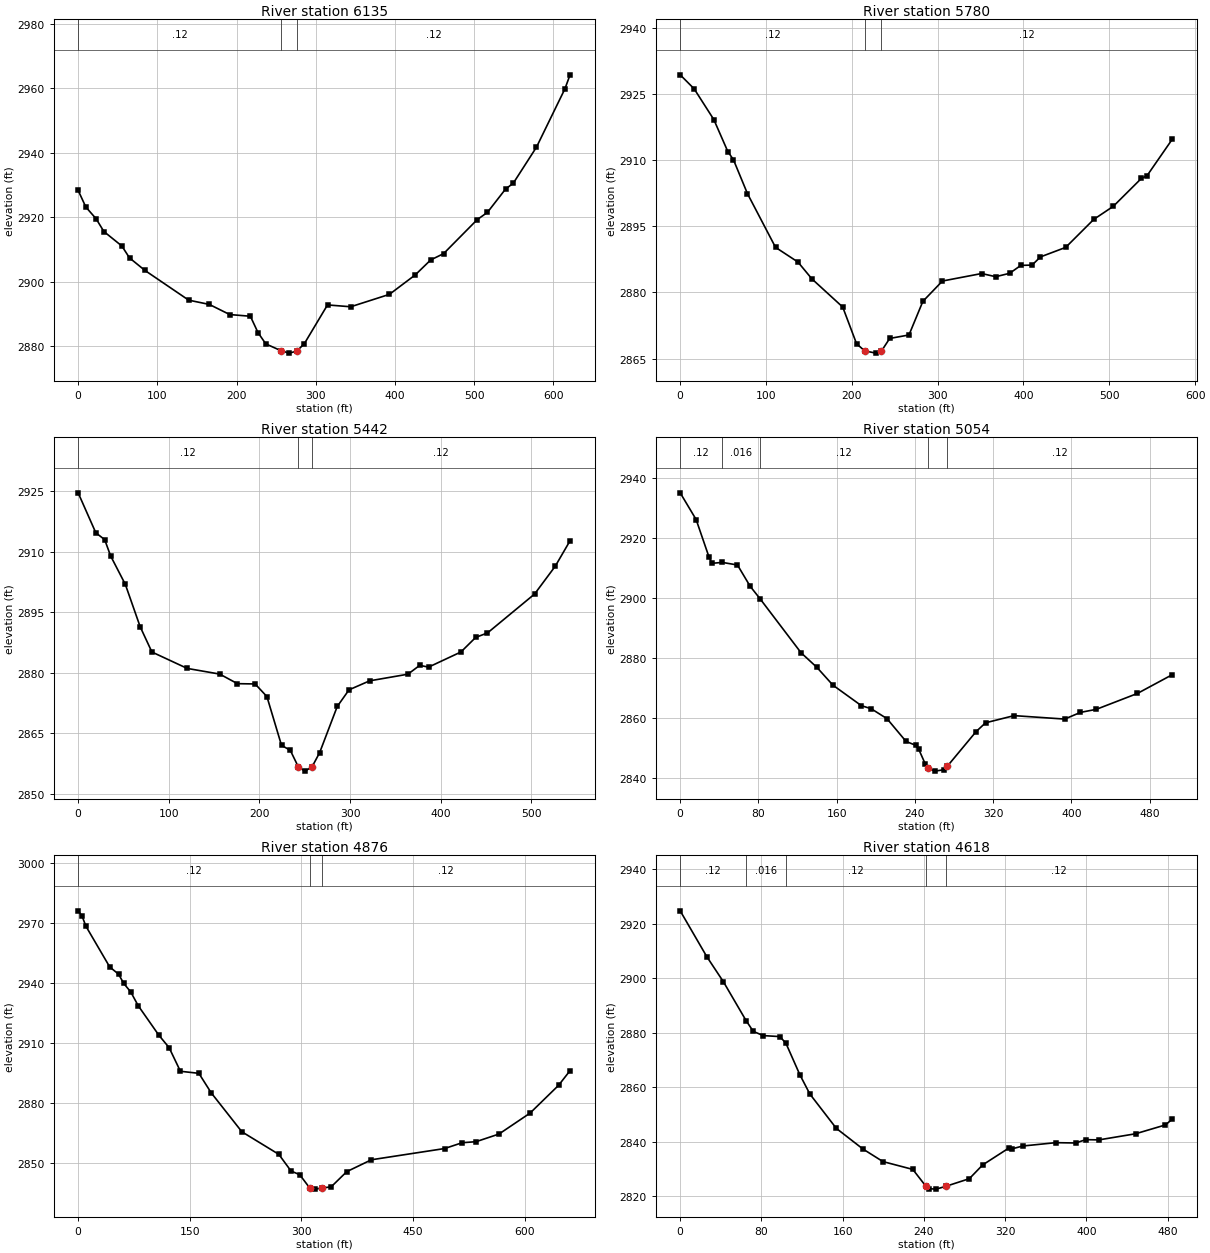
Type RM Length L Ch R = 1 ,6135    ,349.2,354.6,353.7
XS GIS Cut Line= 4
     2105118.243      429953.402     2105322.657      429959.706
     2105451.428      429942.597      2105724.28      429854.347
#Sta/Elev= 30
       0 2928.29     9.7 2923.12    22.7 2919.47    32.5 2915.52    55.2 2911.03
    64.9 2907.33    84.4 2903.44   139.6 2894.23   165.6 2892.91   191.5 2889.76
   217.5 2889.24   227.2 2884.14     237 2880.66   256.5 2878.52   266.2  2877.8
     276 2878.39   285.7 2880.75   314.9 2892.75   344.2 2892.18   393.1 2896.03
   425.7 2902.06   445.2  2906.7   461.5 2908.66   503.9 2919.19   516.9 2921.47
   539.7 2928.68   549.5  2930.5   578.8 2941.69   614.7 2959.77   621.2 2964.12
#Mann= 3 ,-1 , 0
       0     .12       0   256.5     .04       0     276     .12       0
Bank Sta=256.5,276
XS Rating Curve= 0 ,0
Exp/Cntr=0.3,0.1

Type RM Length L Ch R = 1 ,5780    ,332.8,338.4,341.5
XS GIS Cut Line= 4
     2105032.695      430245.165     2105218.199      430261.374
      2105310.95      430271.279     2105604.513      430260.473
#Sta/Elev= 30
       0 2929.38    16.3  2926.2    39.2 2919.23    55.5 2911.98    62.1  2910.1
    78.4 2902.42   111.1 2890.24   137.2 2886.91   153.5 2883.08   189.4 2876.69
   205.5 2868.38   214.9 2866.76     228 2866.24   234.5  2866.7   244.1 2869.57
   266.6 2870.36   282.8 2877.99   305.6  2882.6   351.3  2884.3   367.6 2883.58
   383.9 2884.35     397 2886.15     410 2886.21   419.8 2888.07   449.2 2890.23
   481.9 2896.58   504.7 2899.55   537.4 2905.88   543.9 2906.47   573.2 2914.71
#Mann= 3 ,-1 , 0
       0     .12       0   214.9     .04       0   234.5     .12       0
Bank Sta=214.9,234.5
XS Rating Curve= 0 ,0
Exp/Cntr=0.3,0.1

Type RM Length L Ch R = 1 ,5442    ,385.2,387.2,386.9
XS GIS Cut Line= 4
     2104943.546      430414.459     2105125.447      430501.807
     2105200.188      430558.539     2105410.005      430689.112
#Sta/Elev= 30
       0 2924.65    19.5 2914.74    29.3 2913.04    35.8 2909.02    52.1 2901.93
    68.4 2891.46    81.4 2885.17   120.4  2881.1   156.2  2879.7   175.8 2877.32
   195.3 2877.25   208.3 2874.12   224.4 2862.03   234.1 2860.79   243.1 2856.62
   250.3 2855.63   258.1 2856.69   266.5 2860.22   285.9 2871.66   298.9 2875.79
   321.6 2878.02   363.9 2879.67   376.9 2881.86   386.7 2881.43   422.4 2885.18
   438.7  2888.8   451.7  2889.9   503.7 2899.56   526.5 2906.46   542.8 2912.77
#Mann= 3 ,-1 , 0
       0     .12       0   243.1     .04       0   258.1     .12       0
Bank Sta=243.1,258.1
XS Rating Curve= 0 ,0
Exp/Cntr=0.3,0.1

Type RM Length L Ch R = 1 ,5054    ,178,177.9,177.5
XS GIS Cut Line= 3
     2104757.142      430675.604     2105009.282      430886.321
      2105149.76      430989.879
#Sta/Elev= 30
       0 2934.91    16.3 2926.01    29.3 2913.67    32.5 2911.41   43.04 2911.72
    58.6 2910.85    71.6 2903.74   81.54 2899.66   123.6 2881.61   139.9  2876.7
   156.2  2870.8   185.4 2863.94   195.2 2862.97   211.5 2859.63     231 2852.04
   240.8 2850.76     244  2849.4   250.5 2844.64   253.8 2843.21   260.3 2842.14
     270 2842.61   273.3 2843.81   302.6  2855.3   312.3 2858.25   341.5 2860.64
   393.2 2859.49   409.4 2861.72   425.6 2862.74   467.6 2868.03   503.1 2874.26
#Mann= 5 ,-1 , 0
       0     .12       0   43.04    .016       0   81.54     .12       0
   253.8     .04       0   273.3     .12       0
Bank Sta=253.8,273.3
XS Rating Curve= 0 ,0
Exp/Cntr=0.3,0.1

Type RM Length L Ch R = 1 ,4876    ,257.6,258.5,259
XS GIS Cut Line= 3
2104584.36903751 430780.263011972104923.75112233431039.675754963
2105114.89735401431174.258305839
#Sta/Elev= 30
       0 2976.22     5.2 2973.67    10.4 2968.54    42.4 2948.12    54.3 2944.48
    61.3 2939.83    70.7 2935.57    80.6 2928.74   108.5 2913.87   122.2 2907.69
   137.4 2895.83   162.2  2894.8   178.7 2885.07     220 2865.51   269.6 2854.21
     286 2845.87   297.7    2844   310.9 2837.48   318.8 2836.78   327.52837.353
   339.9 2837.91   360.9 2845.54     394 2851.49   492.4 2857.12   515.9 2860.03
   534.6 2860.55   565.4 2864.38   607.1 2874.85   645.4 2888.76   660.9 2896.15
#Mann= 3 , 0 , 0
       0     .12       0   310.9     .04       0   327.5     .12       0
Bank Sta=310.9,327.5
XS Rating Curve= 0 ,0
Exp/Cntr(USF)=0,0
Exp/Cntr=0.3,0.1

Type RM Length L Ch R = 1 ,4618    ,365.8,361.2,358.8
XS GIS Cut Line= 2
     2104475.285      430997.984     2104840.889      431315.861
#Sta/Elev= 30
       0  2924.7    26.2  2907.9    42.6 2898.67   65.01 2884.38      72 2880.49
    81.8 2878.94    98.2 2878.58  104.14 2876.14   117.8 2864.64   127.7 2857.53
   153.8 2844.92     180 2837.35   199.7 2832.74   229.1 2829.87   242.2 2823.61
   245.5 2822.79   252.1 2822.64   261.9  2823.7   284.8 2826.47   297.9 2831.51
   324.1  2837.8   327.3 2837.45   337.2 2838.44   369.9 2839.68   389.5 2839.56
   399.4 2840.78   412.4  2840.7   448.5 2842.94   477.9 2846.18   484.5 2848.26
#Mann= 5 ,-1 , 0
       0     .12       0   65.01    .016       0  104.14     .12       0
   242.2     .04       0   261.9     .12       0
Bank Sta=242.2,261.9
XS Rating Curve= 0 ,0
Exp/Cntr=0.3,0.1

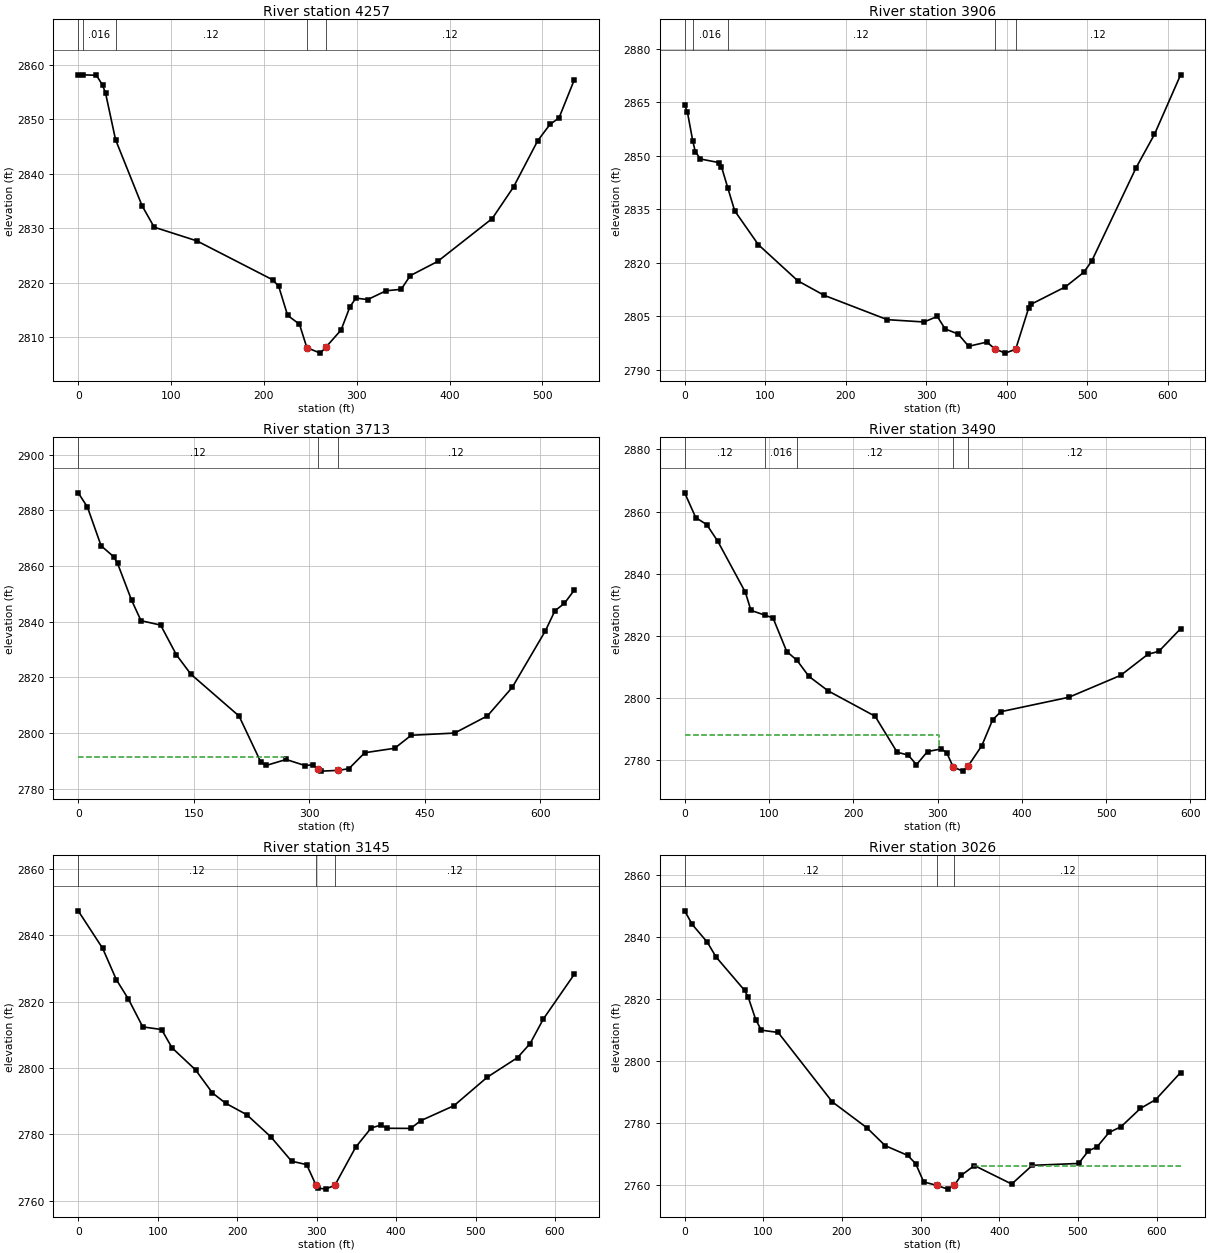
Type RM Length L Ch R = 1 ,4257    ,341.2,351,360.1
XS GIS Cut Line= 4
     2104192.528      431323.065     2104382.534      431411.313
     2104477.987      431448.234     2104676.998      431547.289
#Sta/Elev= 30
       0 2858.14    5.53 2858.18    19.6 2858.09    26.2  2856.3    29.5 2854.78
   40.19 2846.28    68.7 2834.16    81.8  2830.2   127.7 2827.69   209.5 2820.53
   215.9 2819.34   225.5 2814.01   238.3 2812.37  246.24 2808.07   260.7 2807.07
   267.1 2808.23   283.1 2811.32   292.6 2815.57     299 2817.17   311.8 2816.91
   331.5 2818.52   347.8 2818.79   357.6  2821.3     387  2823.9   445.9 2831.79
   468.8 2837.58   494.9 2846.09     508 2849.06   517.8 2850.27   534.1  2857.2
#Mann= 5 ,-1 , 0
       0     .12       0    5.53    .016       0   40.19     .12       0
  246.24     .04       0   267.1     .12       0
Bank Sta=246.24,267.1
XS Rating Curve= 0 ,0
Exp/Cntr=0.3,0.1

Type RM Length L Ch R = 1 ,3906    ,197,193.1,191.6
XS GIS Cut Line= 4
     2104074.562      431442.831     2104284.379      431671.558
     2104342.011      431776.917     2104472.584       431908.39
#Sta/Elev= 30
       0 2864.14     3.3 2862.38    9.96 2854.26    13.1  2851.2    19.6  2849.1
    42.5 2848.09    45.7 2846.92   53.65  2840.9    62.1 2834.56    91.5 2825.05
   140.5 2814.91   173.2 2810.84   251.6 2804.01   297.3 2803.36   313.6 2804.92
   323.4 2801.42   339.6 2799.97   352.6 2796.54   375.3 2797.72     385 2795.83
     398 2794.62     411 2795.71   427.2 2807.35   430.5 2808.38   472.7 2813.21
   495.5  2817.3   505.2 2820.36   560.5 2846.64   583.3 2856.01   615.8 2872.72
#Mann= 5 ,-1 , 0
       0     .12       0    9.96    .016       0   53.65     .12       0
     385     .04       0     411     .12       0
Bank Sta=385,411
XS Rating Curve= 0 ,0
Exp/Cntr=0.3,0.1

Type RM Length L Ch R = 1 ,3713    ,221,222.2,222.6
XS GIS Cut Line= 3
2103932.35915002431558.3530947082104220.48299195431900.331860372
2104375.31589767432021.505438757
#Sta/Elev= 30
       0 2886.24    11.9 2881.17    29.7 2867.22    45.9 2863.33      51 2860.95
    69.3 2847.66    81.5 2840.32     107 2838.74   127.5 2828.04   146.2 2821.12
   208.8 2806.07     237 2789.55     244 2788.33   269.9 2790.47     295 2788.25
   304.5 2788.63   310.7 2787.04   315.8 2786.29   337.8 2786.56   351.4 2787.18
     372  2792.9   410.8  2794.5   432.3 2799.17   488.6 2799.96   531.3 2806.15
   563.4 2816.36   606.3 2836.58   618.8 2843.86   631.2 2846.57   643.8 2851.23
#Mann= 3 , 0 , 0
       0     .12       0   310.7     .04       0   337.8     .12       0
#XS Ineff= 2 , 0
          268.93 2791.38
Permanent Ineff=
       F       F
Bank Sta=310.7,337.8
XS Rating Curve= 0 ,0
Exp/Cntr(USF)=0,0
Exp/Cntr=0.3,0.1

Type RM Length L Ch R = 1 ,3490    ,345.9,344.8,343.8
XS GIS Cut Line= 4
     2103801.711      431760.708     2104033.139      431953.415
     2104061.055      432018.251     2104220.443      432165.033
#Sta/Elev= 30
       0 2866.01    13.1 2858.05    26.2 2855.77    39.3  2850.4      72 2834.01
    78.6 2828.19   94.77 2826.67   104.8 2825.75   121.1 2814.93  133.21 2812.12
   147.3 2806.96   170.2 2802.27   225.9 2794.11   252.1 2782.51   265.2 2781.62
     275 2778.51   288.1 2782.74   304.4 2783.59   310.8 2782.41   318.6 2777.76
     330 2776.44   336.4 2778.14   352.5 2784.61   365.3 2792.91     375 2795.56
   455.8 2800.21   517.3 2807.27   549.6 2814.05   562.6    2815   588.4 2822.29
#Mann= 5 ,-1 , 0
       0     .12       0   94.77    .016       0  133.21     .12       0
   318.6     .04       0   336.4     .12       0
#XS Ineff= 2 , 0
          301.66 2788.09
Permanent Ineff=
       F       F
Bank Sta=318.6,336.4
XS Rating Curve= 0 ,0
Exp/Cntr=0.3,0.1

Type RM Length L Ch R = 1 ,3145    ,105.4,119.9,123.8
XS GIS Cut Line= 3
2103630.16156209431940.9767902362103836.27781892 432257.02171738
2103989.85590491432450.184518684
#Sta/Elev= 30
       0 2847.34    30.8 2836.03      48 2826.61    63.2 2820.76    81.2  2812.4
   104.9  2811.6   118.1 2806.09   147.6 2799.47   168.9 2792.51   185.5 2789.41
   212.1 2785.96   242.4 2779.29   268.5 2771.97   287.5 2770.92   299.3 2764.72
   302.2 2763.86   311.2 2763.55     323 2764.72   349.1 2776.15   368.7 2781.98
   380.7 2782.81   389.2 2781.87   418.4 2781.83     431 2784.15   472.9 2788.68
   514.8 2797.26   552.9 2803.15   568.7 2807.39   585.4  2814.8   624.1 2828.17
#Mann= 3 , 0 , 0
       0     .12       0   299.3     .04       0     323     .12       0
Bank Sta=299.3,323
XS Rating Curve= 0 ,0
Exp/Cntr(USF)=0,0
Exp/Cntr=0.3,0.1

Type RM Length L Ch R = 1 ,3026    ,252.3,229.5,224.1
XS GIS Cut Line= 4
2103572.88146521431956.3900694072103716.18133901432180.173433968
2103682.81013553432305.8062000382103800.59085372432508.977938916
#Sta/Elev= 30
       0 2848.33     9.6 2843.94    28.6 2838.27      40 2833.42    76.1 2822.71
    80.8 2820.49    90.3  2813.3    97.4 2809.87   118.8 2809.13   187.7 2786.75
   231.6 2778.42     255 2772.63   283.5 2769.51   293.7 2766.85   303.9 2760.96
   320.8 2759.81   334.4 2758.63  342.81 2759.83   351.4 2763.03   368.4 2766.23
   415.8 2760.27     442  2766.3   500.9  2766.9   513.4 2770.96   524.4 2772.26
   539.6  2776.9   554.8 2778.73   579.4 2784.62     599  2787.5   630.6 2796.22
#Mann= 3 , 0 , 0
       0     .12       0   320.8     .04       0  342.81     .12       0
#XS Ineff= 2 , 0
                          367.15         2766.04
Permanent Ineff=
       F       F
Bank Sta=320.8,342.81
XS Rating Curve= 0 ,0
Exp/Cntr(USF)=0,0
Exp/Cntr=0.3,0.1

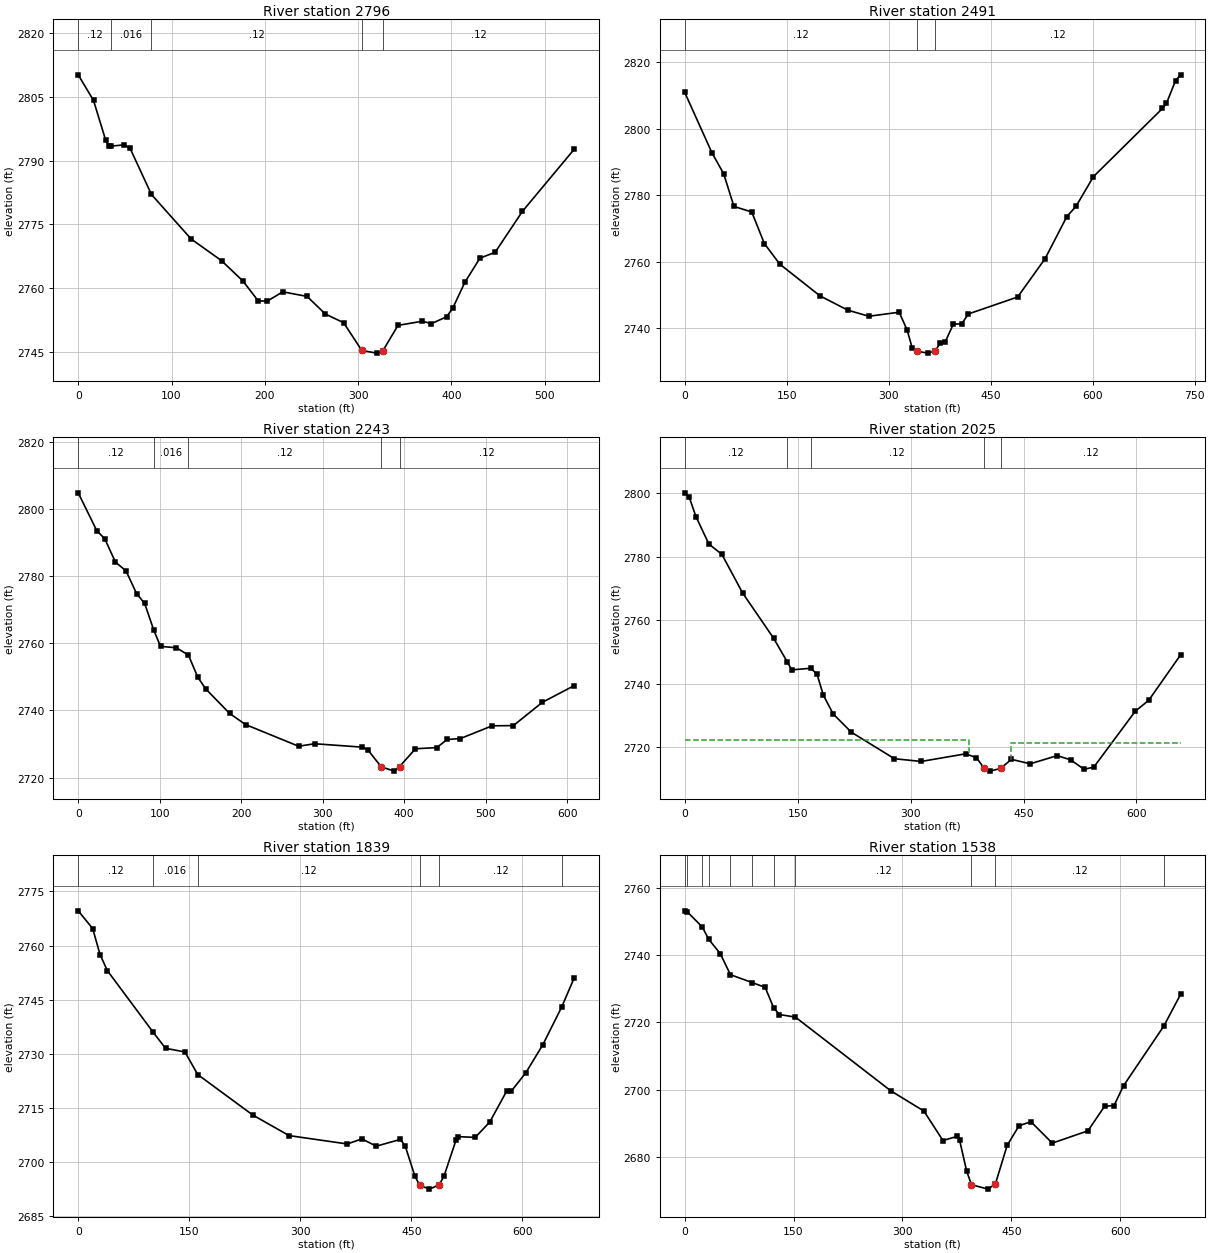
Type RM Length L Ch R = 1 ,2796    ,295.3,304.9,310.3
XS GIS Cut Line= 4
     2103382.077      432176.739     2103541.466      432404.566
     2103611.705      432437.885     2103734.173      432563.955
#Sta/Elev= 30
       0 2810.18    16.4 2804.16    29.4 2794.84    32.7 2793.38   34.67  2793.4
    49.1 2793.72    55.6 2792.91   78.46 2782.06     121  2771.6   153.7 2766.48
   176.6  2761.7     193 2757.02   202.8    2757   219.2 2759.17   245.3 2758.09
     265 2753.94   284.5 2751.91     304 2745.38   320.2 2744.76   326.6 2745.33
   342.8 2751.29   368.8 2752.25   378.6  2751.7   394.8 2753.29   401.4 2755.29
   414.4 2761.39   430.6 2767.09   446.9 2768.46   476.2  2778.1   531.6 2792.67
#Mann= 5 ,-1 , 0
       0     .12       0   34.67    .016       0   78.46     .12       0
     304     .04       0   326.6     .12       0
Bank Sta=304,326.6
XS Rating Curve= 0 ,0
Exp/Cntr=0.3,0.1

Type RM Length L Ch R = 1 ,2491    ,248.7,248.2,248.8
XS GIS Cut Line= 3
2103206.69470462432304.5246007622103415.23914432432683.696309318
2103615.88417343432901.720041737
#Sta/Elev= 30
       0 2810.88    39.9 2792.78    57.4 2786.36    72.4 2776.59    98.6 2774.91
   117.2 2765.41   139.8 2759.25   198.8 2749.73   239.6 2745.43   270.8 2743.59
   315.3  2744.8     327 2739.44   334.6 2733.96     342 2733.09     357 2732.51
   368.5 2733.23   375.7 2735.62   383.2    2736     395 2741.25   407.1 2741.27
   416.9 2744.27   489.4 2749.37   529.8 2760.89   561.8 2773.56   575.3 2776.64
   600.8 2785.53   702.3 2806.03   708.1 2807.52   721.6 2814.42     729 2816.13
#Mann= 3 , 0 , 0
       0     .12       0     342     .04       0   368.5     .12       0
Bank Sta=342,368.5
XS Rating Curve= 0 ,0
Exp/Cntr(USF)=0,0
Exp/Cntr=0.3,0.1

Type RM Length L Ch R = 1 ,2243    ,217.9,217.6,219.4
XS GIS Cut Line= 3
     2103004.767      432416.273     2103202.877      432798.085
     2103284.823      432956.573
#Sta/Elev= 30
       0  2804.8    22.8 2793.52    32.6 2791.11    45.6  2784.2    58.7 2781.52
    71.7 2774.75    81.5 2771.87   92.82 2763.83     101 2759.07   120.6 2758.64
  135.32 2756.44   146.6 2749.93   156.4 2746.42   185.8 2739.08   205.3 2735.78
   270.5 2729.31     290 2730.06   348.7 2729.04   355.2 2728.29   371.9 2723.18
   387.8  2721.9   394.3 2723.25   413.9 2728.57   439.9  2728.9   452.9 2731.33
   469.1 2731.61     508  2735.4     534 2735.46   569.6  2742.4   608.6 2747.36
#Mann= 5 ,-1 , 0
       0     .12       0   92.82    .016       0  135.32     .12       0
   371.9     .04       0   394.3     .12       0
Bank Sta=371.9,394.3
XS Rating Curve= 0 ,0
Exp/Cntr=0.3,0.1

Type RM Length L Ch R = 1 ,2025    ,184.3,186.5,186.1
XS GIS Cut Line= 3
2102846.65217425432435.603019632 2102952.8841139432776.533430582
2103072.70385977433053.230575701
#Sta/Elev= 30
       0 2800.06     6.1 2798.66      15 2792.55    32.2 2783.94    49.4 2780.72
    76.9 2768.58   118.1 2754.33   136.5 2746.79   142.2 2744.39  167.44 2744.89
   175.7 2743.04   184.2 2736.41   197.2 2730.53   221.2  2724.8   278.5 2716.45
     314 2715.58   373.1 2717.98   387.4 2716.77   397.1 2713.66   405.2 2712.54
   419.6 2713.38   433.8 2716.25   458.9 2714.84   494.6 2717.41   512.5 2716.09
   530.4 2713.12   543.3  2713.8   598.3 2731.35   616.2 2734.81   658.6  2749.1
#Mann= 5 ,-1 , 0
       0     .12       0   136.5    .016       0  167.44     .12       0
   397.1     .04       0   419.6     .12       0
#XS Ineff= 2 , 0
          377.52 2722.43  433.41         2721.41
Permanent Ineff=
       F       F
Bank Sta=397.1,419.6
XS Rating Curve= 0 ,0
Exp/Cntr=0.3,0.1

Type RM Length L Ch R = 1 ,1839    ,285.5,301.1,303.8
XS GIS Cut Line= 4
     2102708.502      432466.701     2102782.344      432835.906
     2102843.578      432972.782     2102866.991      433114.161
#Sta/Elev= 30
       0 2769.63    19.6  2764.7    29.5  2757.5    39.3 2753.07  101.19 2735.97
   117.9 2731.52   144.1  2730.5  161.43 2724.24   235.7 2713.02   284.8 2707.31
   363.4 2704.99     383  2706.4   402.6 2704.38   435.2 2706.26   441.7 2704.38
   454.8 2696.02   461.3 2693.53   474.3 2692.47   487.4 2693.65   493.9 2696.01
   510.2 2706.02   513.4 2707.02   536.2 2706.81   555.8 2711.07   578.6 2719.63
   585.1 2719.68   604.6 2724.76   627.4 2732.47  652.97 2742.95   669.8 2751.02
#Mann= 6 ,-1 , 0
       0     .12       0  101.19    .016       0  161.43     .12       0
   461.3     .04       0   487.4     .12       0  652.97    .016       0
Bank Sta=461.3,487.4
XS Rating Curve= 0 ,0
Exp/Cntr=0.3,0.1

Type RM Length L Ch R = 1 ,1538    ,170.5,163.6,160.4
XS GIS Cut Line= 4
     2102607.646      432473.905     2102563.522       432807.09
     2102531.104      432947.568      2102541.91      433150.181
#Sta/Elev= 30
       0  2753.1    3.44 2752.83    24.2 2748.32   33.24  2744.6      49 2740.41
   63.03 2734.13   92.83 2731.81   110.9 2730.37  122.62 2724.26   130.5  2722.3
  152.42 2721.55   283.9 2699.66   329.6 2693.63   355.8 2684.89   375.4 2686.13
   378.7 2685.02   388.5 2675.75   395.1 2671.77     418 2670.46   428.1 2672.03
   444.2 2683.43   460.6 2689.28     477 2690.48   506.4 2684.12   555.5 2687.77
   578.4 2695.05   591.5 2695.29   604.6 2701.18  660.07 2718.89   683.2  2728.3
#Mann= 11 ,-1 , 0
       0     .06       0    3.44     .12       0    24.2     .06       0
   33.24     .12       0   63.03     .06       0   92.83     .12       0
  122.62    .016       0  152.42     .12       0   395.1     .04       0
   428.1     .12       0  660.07    .016       0
Bank Sta=395.1,428.1
XS Rating Curve= 0 ,0
Exp/Cntr=0.3,0.1