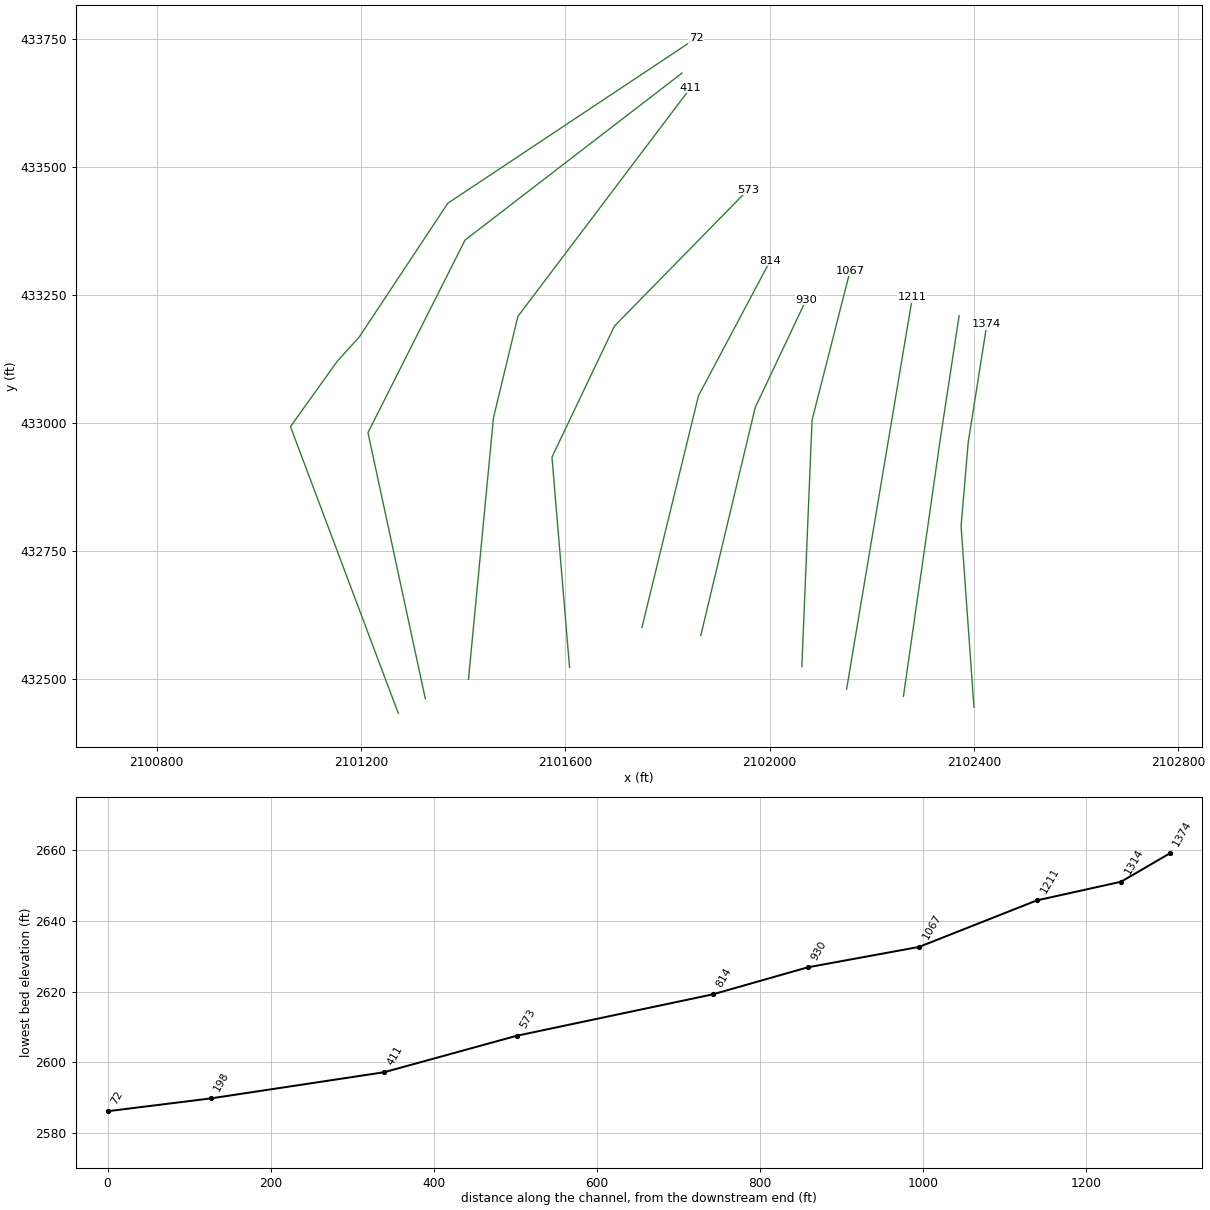
HEC-RAS study IMPRVMTBR.prj: IMPRVMTBR

--- IMPRVMTBR.g01 (geometry) --- (continued)

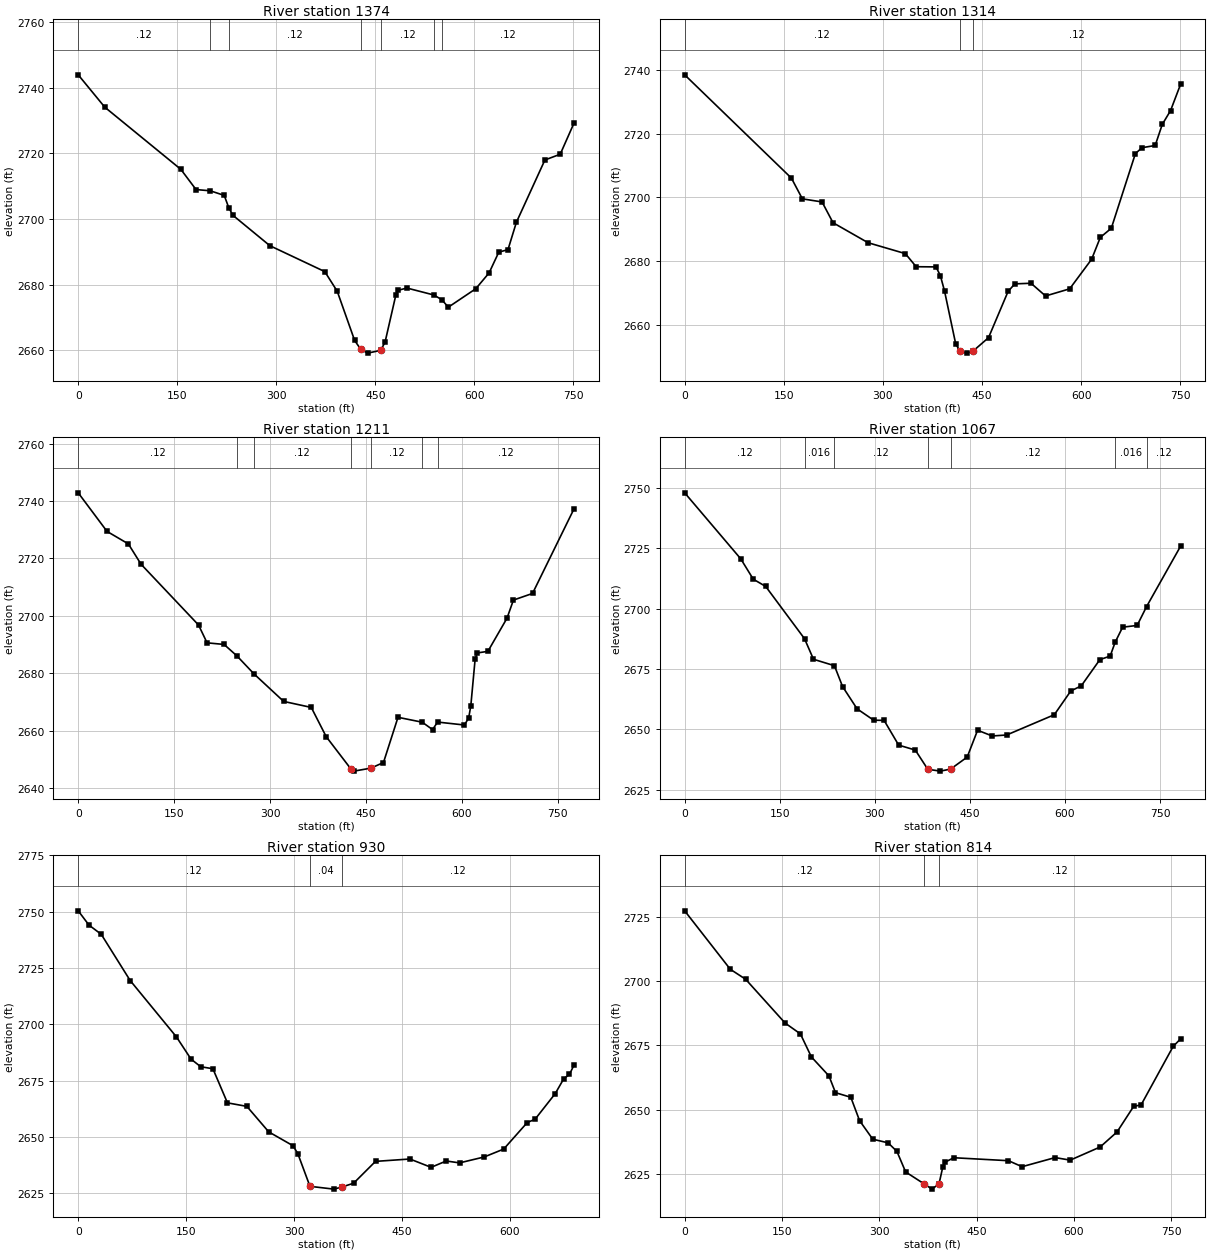
Type RM Length L Ch R = 1 ,1374    ,60.2,59.7,59.7
XS GIS Cut Line= 4
 2102399.9493489432445.9186792892102374.73405111432798.932848358
2102388.74254989432962.832283998 2102425.1646467433192.571663868
#Sta/Elev= 30
       0 2743.92    40.2 2734.07   155.4 2715.13   178.4 2708.97     200 2708.59
   221.1 2707.19   227.9 2703.49   234.3 2701.12   290.2 2691.87   373.4 2683.97
   392.2    2678   418.6 2662.99     428 2660.27   438.3 2659.14   458.1 2659.98
   464.7 2662.53   481.1 2676.94   484.4 2678.28   497.7 2678.97   538.8 2676.84
   550.7 2675.38   560.5 2673.14     602 2678.75   622.2 2683.58   636.9 2689.91
   650.8 2690.66   663.5 2698.98   706.7 2717.98   729.9 2719.73     751 2729.32
#Mann= 7 ,-1 , 0
       0     .12       0     200    .016       0   227.9     .12       0
     428     .04       0   458.1     .12       0   538.8    .016       0
   550.7     .12       0
Bank Sta=428,458.1
XS Rating Curve= 0 ,0
Exp/Cntr(USF)=0,0
Exp/Cntr=0.3,0.1

Type RM Length L Ch R = 1 ,1314    ,102.6,103.2,103.7
XS GIS Cut Line= 3
2102261.92519747432467.2524590172102334.59977494432972.814737091
2102370.93706368433209.797054938
#Sta/Elev= 30
       0 2738.43   161.5 2706.03   178.1 2699.52   207.9 2698.55   224.5 2692.03
   277.5 2685.76   333.9 2682.34   350.3 2678.23   380.3 2678.17   386.9 2675.46
   393.2 2670.63   410.1 2654.05   416.7 2651.71   426.7 2651.12   436.6  2651.8
   459.8 2655.97   489.4 2670.48   499.6 2672.85   524.1 2673.04   546.1 2669.05
   582.6 2671.29   615.8 2680.56     629 2687.44   645.6 2690.29   682.1 2713.74
   692.1 2715.57     712 2716.26   722.7 2722.86   735.3 2727.22   750.5  2735.5
#Mann= 3 , 0 , 0
       0     .12       0   416.7     .04       0   436.6     .12       0
Bank Sta=416.7,436.6
XS Rating Curve= 0 ,0
Exp/Cntr(USF)=0,0
Exp/Cntr=0.3,0.1

Type RM Length L Ch R = 1 ,1211    ,142.7,144.5,146.7
XS GIS Cut Line= 2
2102150.59807075 432480.939926222102279.47625946433245.803959204
#Sta/Elev= 30
       0 2742.89    45.1 2729.43    78.4 2725.08    98.3 2717.98   188.2 2696.79
   201.5 2690.58   228.1 2690.02   248.1 2686.05   274.7 2679.79   321.3 2670.15
   364.5 2668.05   387.8 2657.87   426.1  2646.7   431.1 2645.84   457.7 2646.88
   477.4 2648.84   500.1 2664.61     538  2662.9   554.2 2660.32     562 2662.95
   604.1 2661.92   610.7 2664.44     614 2668.66   620.7 2684.81     624 2687.05
   640.7 2687.61   670.6 2699.18   680.6 2705.49   710.5  2707.8   775.6 2737.41
#Mann= 7 ,-1 , 0
       0     .12       0   248.1    .016       0   274.7     .12       0
   426.1     .04       0   457.7     .12       0     538    .016       0
     562     .12       0
Bank Sta=426.1,457.7
XS Rating Curve= 0 ,0
Exp/Cntr(USF)=0,0
Exp/Cntr=0.3,0.1

Type RM Length L Ch R = 1 ,1067    ,139.4,136.5,129.9
XS GIS Cut Line= 3
     2102062.999      432524.633      2102083.01      433006.012
     2102157.496      433297.285
#Sta/Elev= 30
       0 2747.93    88.5 2720.58   108.2 2712.16   127.8 2709.16  189.14 2687.48
   203.2 2678.99  236.24 2676.33   249.1 2667.68     272 2658.46   298.2 2653.75
   314.6 2653.68   337.6 2643.43   363.8 2641.39   383.5 2633.44   403.1 2632.66
   419.5  2633.5   445.7 2638.48   462.1  2649.6   485.1 2647.22   507.9 2647.62
   583.1 2656.02   609.2 2665.88   625.6 2667.96     655 2678.84   671.3 2680.32
  679.07 2686.02   690.9 2692.28   713.8    2693  728.75 2700.84   782.4 2725.85
#Mann= 7 ,-1 , 0
       0     .12       0  189.14    .016       0  236.24     .12       0
   383.5     .04       0   419.5     .12       0  679.07    .016       0
  728.75     .12       0
Bank Sta=383.5,419.5
XS Rating Curve= 0 ,0
Exp/Cntr=0.3,0.1

Type RM Length L Ch R = 1 ,930     ,119.9,116.5,114.7
XS GIS Cut Line= 3
2101865.32916892432586.1922073212101971.69264328433030.495328066
2102071.32425217433240.529530601
#Sta/Elev= 30
       0 2750.33      15 2743.99      32 2739.92    72.2 2719.42   136.6 2694.37
   156.8 2684.55   170.3 2681.17   187.2 2680.28   207.4 2665.15   234.4 2663.59
   264.8 2652.28   298.5 2646.14   305.2 2642.65   322.1 2628.12   355.3 2626.88
     367 2627.86   382.8 2629.51   413.2 2639.19     461 2640.24   490.5 2636.55
   511.5 2639.36     530 2638.52   564.4 2641.16   591.4 2644.65   624.1 2656.41
     635 2657.89     663 2669.25   674.9 2675.87   682.7 2677.74   689.3 2682.04
#Mann= 3 , 0 , 0
       0     .12       0   322.1     .04       0     367     .12       0
Bank Sta=322.1,367
XS Rating Curve= 0 ,0
Exp/Cntr(USF)=0,0
Exp/Cntr=0.3,0.1

Type RM Length L Ch R = 1 ,814     ,244.7,240.5,238.7
XS GIS Cut Line= 3
2101750.04339092432601.5424391312101860.63513925433053.388725159
2102001.24464784433317.229039029
#Sta/Elev= 30
       0  2727.3    70.3  2704.6    93.9 2700.73   154.7 2683.73   178.3 2679.51
   195.2 2670.58   222.3 2663.19   232.4 2656.68     256 2654.89   269.5 2645.82
   289.8 2638.61   313.4  2637.2     327 2633.89   340.5 2625.89     369 2621.25
     381 2619.22   391.9 2621.25   397.9    2628   401.3 2629.71   414.8 2631.41
   498.9 2630.26   519.9 2627.93   570.8 2631.47   594.1 2630.48   640.2 2635.58
   666.2 2641.41   691.7 2651.31   703.4 2651.97   752.7 2674.64   764.2 2677.59
#Mann= 3 , 0 , 0
       0     .12       0     369     .04       0   391.9     .12       0
Bank Sta=369,391.9
XS Rating Curve= 0 ,0
Exp/Cntr(USF)=0,0
Exp/Cntr=0.5,0.3

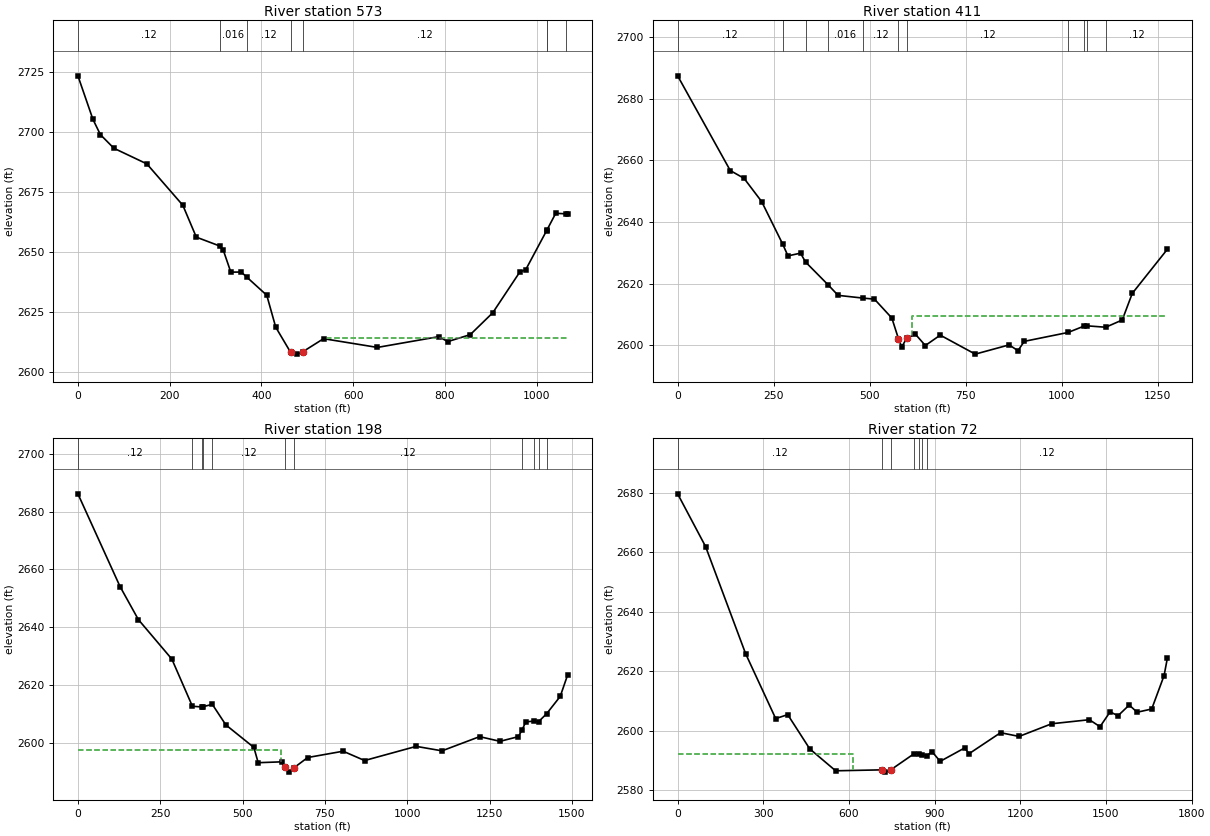
Type RM Length L Ch R = 1 ,573     ,162.9,162.5,164.8
XS GIS Cut Line= 4
     2101608.301      432523.521     2101573.838      432933.749
     2101696.128      433189.447     2101957.385      433455.151
#Sta/Elev= 30
       0 2723.28    32.7 2705.19      49 2698.82    78.4 2693.15   150.3 2686.64
   228.7 2669.43   258.1 2656.16  309.32 2652.47   316.9 2650.75   333.3 2641.61
   356.1 2641.64   368.6 2639.45   411.7 2631.98   431.2  2618.7   463.8 2608.18
   476.8 2607.49   489.9 2608.44   535.5 2613.92   652.8 2610.28   786.6 2614.76
   806.2  2612.7   855.3  2615.6   904.3  2624.7   963.1 2641.61   976.2 2642.64
 1021.73 2658.88 1021.93 2658.96  1041.6 2666.09 1063.86 2665.86  1067.7 2665.71
#Mann= 8 ,-1 , 0
       0     .12       0  309.32    .016       0   368.6     .12       0
   463.8     .04       0   489.9     .12       0 1021.73     .06       0
 1021.93    .016       0 1063.86     .12       0
#XS Ineff= 2 , 0
       0                  543.52       0  2614.2
Permanent Ineff=
       F       F
Bank Sta=463.8,489.9
XS Rating Curve= 0 ,0
Exp/Cntr=0.5,0.3

Type RM Length L Ch R = 1 ,411     ,217.7,212.5,210.7
XS GIS Cut Line= 4
     2101410.414      432500.175      2101459.33      433010.459
     2101507.134      433208.347       2101845.1       433654.15
#Sta/Elev= 30
       0 2687.43   137.1 2656.71     173 2654.18   218.8 2646.65  273.76 2632.81
   287.3 2629.03     320 2629.92   333.1 2627.05  392.45 2619.57   417.9 2616.23
  481.46 2615.36   512.6    2615   557.9 2608.87  574.99 2602.21   583.7 2599.53
   596.6 2602.32   619.3 2603.62   645.1 2599.96   683.9 2603.33   775.1 2597.17
   863.4 2600.17   886.3 2598.28   902.7 2601.31 1016.98  2604.2 1059.06  2606.3
 1065.87 2606.35 1114.76 2605.89  1157.9 2608.24    1184 2616.87  1275.6 2631.21
#Mann= 11 ,-1 , 0
       0     .12       0  273.76    .016       0   333.1     .12       0
  392.45    .016       0  481.46     .12       0  574.99     .04       0
   596.6     .12       0 1016.98    .016       0 1059.06     .12       0
 1065.87    .016       0 1114.76     .12       0
#XS Ineff= 2 , 0
                          610.85          2609.4
Permanent Ineff=
       F       F
Bank Sta=574.99,596.6
XS Rating Curve= 0 ,0
Exp/Cntr=0.5,0.3

Type RM Length L Ch R = 1 ,198     ,126.5,126.6,121
XS GIS Cut Line= 4
     2101325.922      432462.376     2101213.637      432981.554
     2101403.743      433357.318     2101828.424      433683.055
#Sta/Elev= 30
       0 2686.23   127.9  2654.1   183.6 2642.64   285.3 2628.94   347.7 2612.59
  377.92 2612.34  379.08 2612.41  408.14 2613.26   449.2 2606.14   534.4 2598.32
   547.5 2593.03   619.3 2593.33   629.1 2591.43   642.2 2589.76   655.2 2591.18
   697.7 2594.82   805.4 2597.01   870.7 2593.78  1027.4 2598.69  1105.7 2597.14
  1219.9 2602.06  1281.9 2600.44  1337.4 2602.05 1348.82 2604.36  1360.2  2607.2
 1386.04 2607.44  1399.1 2607.27 1423.27 2609.98  1464.7    2616  1487.5 2623.54
#Mann= 11 ,-1 , 0
       0     .12       0   347.7    .016       0  377.92     .12       0
  379.08     .06       0  408.14     .12       0   629.1     .04       0
   655.2     .12       0 1348.82    .016       0 1386.04     .12       0
  1399.1    .016       0 1423.27     .12       0
#XS Ineff= 2 , 0
          615.95 2597.52     800         2596.44
Permanent Ineff=
       F       F
Bank Sta=629.1,655.2
XS Rating Curve= 0 ,0
Exp/Cntr=0.3,0.1

Type RM Length L Ch R = 1 ,72      ,70,72,76
XS GIS Cut Line= 6
2101273.05256394432433.8193855892101061.93571511432993.234019993
2101153.27191981433120.4650756242101196.66333439433168.290408545
2101369.98998641433429.1154579842101855.60627156433750.860841149
#Sta/Elev= 30
       02679.683  97.9162661.949 238.1842625.918 343.3842604.126 385.4652605.455
 462.6122593.949 553.3572586.577 716.0542586.894 726.5162586.128 745.7772586.866
  827.572592.291  845.29 2592.36 855.1442591.917 873.6882591.664 890.5972593.042
 919.377 2589.751004.8332594.247 1020.59 2592.331130.8872599.3851195.6992598.129
1309.8322602.3921441.7452603.7481479.0622601.4011514.4832606.3891542.0322605.077
1581.3882608.6871608.937 2606.26  1660.12607.3511703.3912618.5841715.1692624.572
#Mann= 7 ,-1 , 0
       0     .12       0 716.054     .04       0 745.777     .12       0
  827.57    .016       0  845.29     .12       0 855.144    .016       0
 873.688     .12       0
#XS Ineff= 2 , 0
          613.95 2592.34
Permanent Ineff=
       F       F
Bank Sta=716.054,745.777
XS Rating Curve= 0 ,0
Exp/Cntr(USF)=0,0
Exp/Cntr=0.3,0.1
LCMann Table=0

Chan Stop Cuts=-1
Use User Specified Reach Order=0
Composite Channel Slope=5